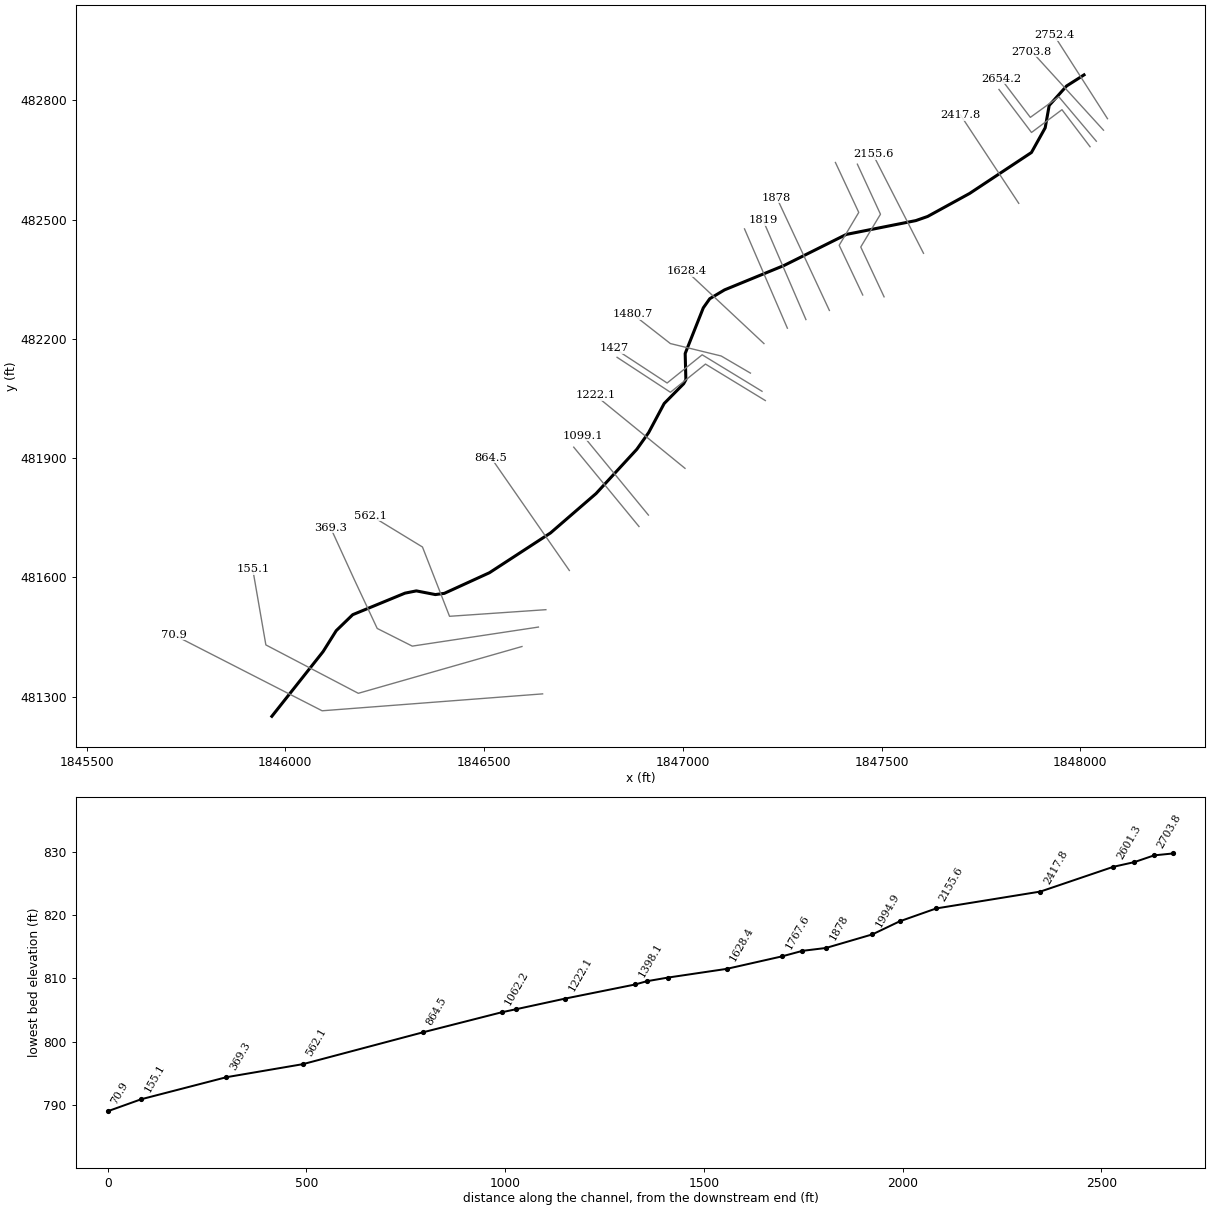
--- EIGHTMILFK.prj (project) ---

Proj Title=EIGHTMILFK
Current Plan=p01
Default Exp/Contr=0,0
English Units
Geom File=g01
Flow File=f01
Plan File=p01
BEGIN DESCRIPTION:
END DESCRIPTION:
DSS Export Rating Curves= 0
DSS Export Rating Curve Sorted= 0
DSS Export Volume Flow Curves= 0
DXF OffsetX= 0
DXF OffsetY= 0
DXF ScaleX= 0
DXF ScaleY= 0

--- EIGHTMILFK.p01 (plan) ---

Plan Title=Floodplain
Program Version=4.00
Geom File=g01
Flow File=f01
K Sum by GR=0
Std Step Tol=0.01
Critical Tol=0.01
Num of Std Step Trials=20
Max Error Tol=0.3
Flow Tol Ratio=0.001
Split Flow NTrial=30
Split Flow Tol=0.02
Split Flow Ratio=0.02
Log Output Level=0
Friction Slope Method=1
Unsteady Friction Slope Method=2
Unsteady Bridges Friction Slope Method=1
Global Log Level=0
CheckData=False
Run HTab=0
Run UNet=0
Run PostProcess=0
UNET Theta=0
UNET Theta Warmup=0
UNET ZTol=0
UNET ZSATol=0
UNET MxIter=0
UNET MaxInSteps=0
UNET DtIC=0
UNET DtMin=0
UNET MaxCRTS=0
UNET WFStab=0
UNET SFStab=0
UNET WFX=0
UNET SFX=0
UNET DSS MLevel=0
UNET DZMax Abort=0
UNET Convert EG Bridges=0
UNET Use Existing IB Tables=0
UNET Froude Limit=0
UNET Froude Power=0
Write IC File=0
Echo Input=False
Echo Output=False
Write Detailed=0

--- EIGHTMILFK.f01 (steady flow) ---

Flow Title=NFF Regression Equation
Program Version=4.10
Number of Profiles= 1
Profile Names=P100yr
River Rch & RM=EIGHTMILFK,Main            ,2752.4
921.3325
River Rch & RM=EIGHTMILFK,Main            ,864.5
960.7111
Boundary for River Rch & Prof#=EIGHTMILFK,Main            , 1
Up Type= 0
Dn Type= 3
Dn Slope=0.025
DSS Import GetInterval= 0
DSS Import GetPeak= 0
DSS Import FillOption= 0

--- EIGHTMILFK.g01 (geometry) ---

Geom Title=USGS 10m DEM
Program Version=4.10

River Reach=EIGHTMILFK      ,Main
Reach XY= 30
     1848009.242      482864.159      1847965.36       482836.25
      1847921.61      482787.291     1847911.541      482731.041
     1847876.965      482668.921     1847721.548      482566.004
       1847615.8      482508.003     1847586.092      482497.613
     1847411.283      482462.856     1847255.086      482384.938
     1847104.842      482323.308     1847067.689      482301.085
     1847051.474      482278.134     1847005.884      482163.238
      1847007.62      482097.266     1847002.064      482087.197
     1846953.106      482037.544     1846913.939       481964.21
     1846884.217      481922.266     1846781.735      481811.003
     1846667.099      481711.854      1846513.56      481611.816
     1846399.949      481559.872     1846377.449      481556.816
     1846329.595      481566.089      1846301.06      481560.427
     1846169.523      481506.235     1846128.013      481466.004
      1846095.05      481413.447     1845966.064      481250.558

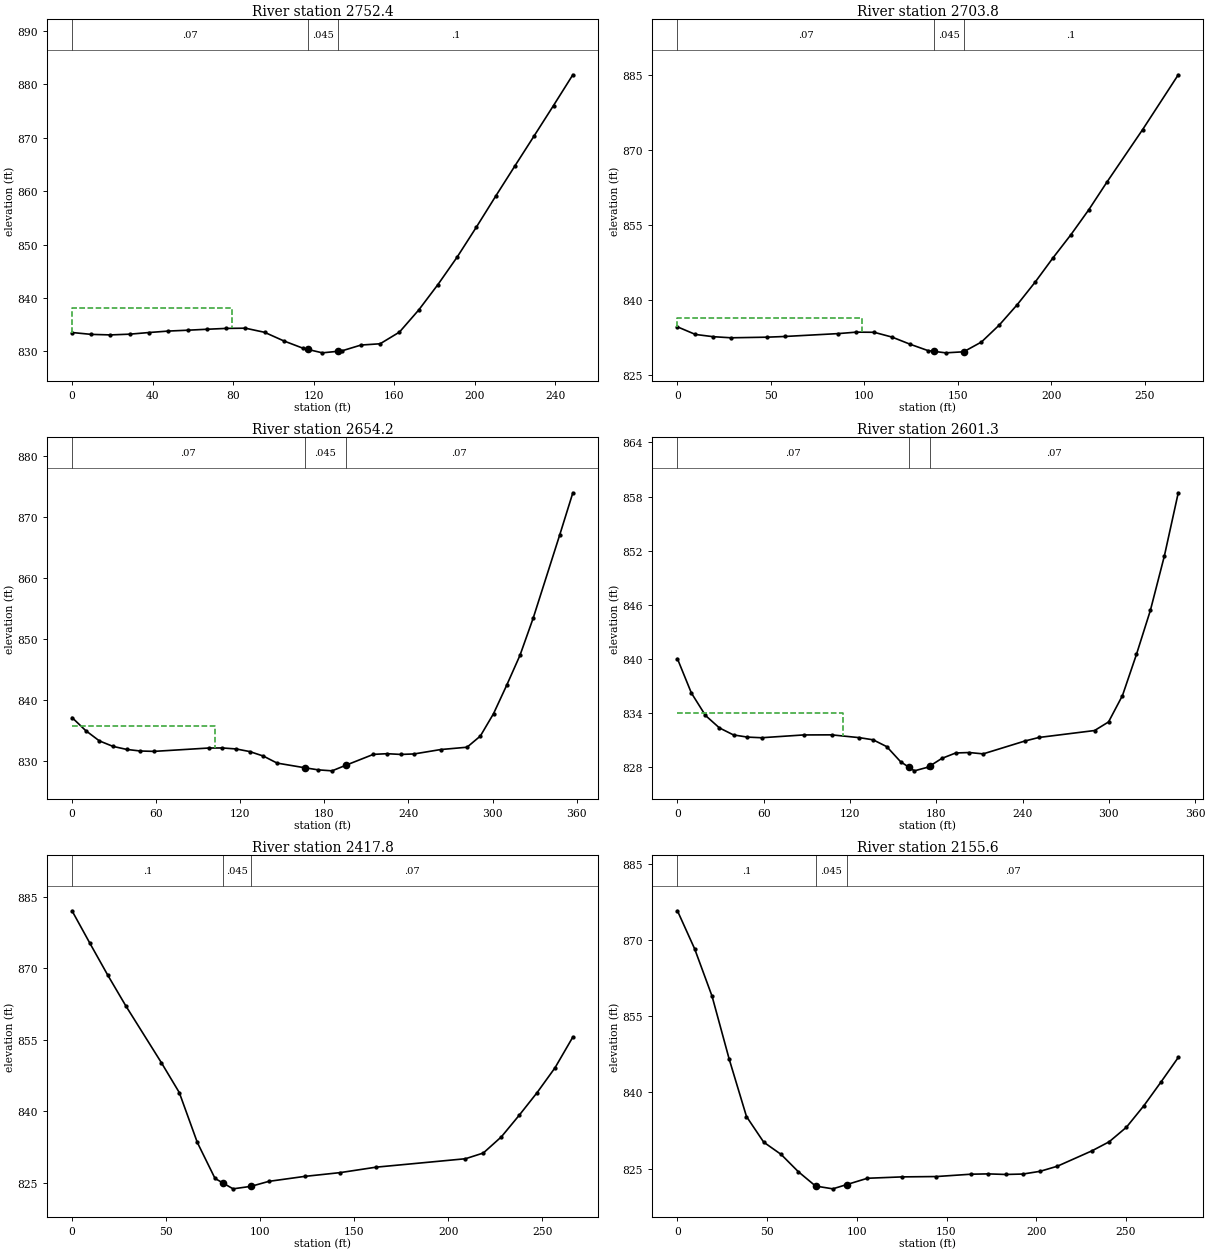
Type RM Length L Ch R = 1 ,2752.4  ,44.8,48.7,52.5
XS GIS Cut Line= 2
     1848068.221       482754.07     1847934.193      482963.526
#Sta/Elev= 29
       0  833.51     9.6  833.16    19.1  833.06    28.7   833.2    38.3  833.51
    47.8  833.78    57.4  833.94      67  834.12    76.5  834.28    86.1  834.32
    95.6  833.55   105.2  831.93   114.8  830.55     117  830.35   124.3   829.7
     132  829.99   133.9  830.06   143.5  831.16     153   831.4   162.6  833.59
   172.2  837.75   181.7   842.5   191.3  847.68   200.8  853.27   210.4  859.08
     220  864.78   229.5  870.38   239.1  876.06   248.7  881.82
#Mann= 3 , 0 , 0
       0     .07       0     117    .045       0     132      .1       0
#XS Ineff= 2 , 0
           79.21  838.08
Permanent Ineff=
       F       F
Bank Sta=117,132
XS Rating Curve= 0 ,0
Exp/Cntr=0.3,0.1

Type RM Length L Ch R = 1 ,2703.8  ,27,49.6,96.9
XS GIS Cut Line= 2
     1848058.228      482725.079     1847877.673      482922.995
#Sta/Elev= 25
       0  834.59     9.6  833.07    19.1  832.62    28.7   832.4    47.8  832.52
    57.4  832.66    86.1  833.24    95.7  833.53   105.2   833.5   114.8  832.54
   124.4  831.12     134  829.84   137.3  829.68   143.5  829.39   153.1   829.6
   162.6  831.55   172.2  834.97   181.8  839.04   191.4  843.56   200.9  848.39
   210.5  853.03   220.1  858.04   229.6  863.46   248.8  874.02   267.9     885
#Mann= 3 , 0 , 0
       0     .07       0   137.3    .045       0   153.1      .1       0
#XS Ineff= 2 , 0
            98.9  836.34
Permanent Ineff=
       F       F
Bank Sta=137.3,153.1
XS Rating Curve= 0 ,0
Exp/Cntr=0.3,0.1

Type RM Length L Ch R = 1 ,2654.2  ,37.9,52.9,47.6
XS GIS Cut Line= 4
     1848040.173      482697.301     1847945.838       482809.07
       1847874.2      482757.315     1847799.931      482854.976
#Sta/Elev= 30
       0  837.07     9.8  834.92    19.5  833.24    29.2  832.34      39  831.84
    48.8  831.58    58.5  831.52    97.5  832.07   107.3  832.08     117  831.92
   126.8  831.49   136.5  830.75   146.3   829.6   165.9  828.84   175.7  828.49
   185.5  828.33   195.4  829.25     215  831.03   224.8  831.14   234.6  831.02
   244.1   831.1     263  831.82   281.8   832.2   291.3  834.03   300.7   837.7
   310.1  842.36   319.6  847.28     329  853.36   347.9  866.98   357.3  873.91
#Mann= 3 , 0 , 0
       0     .07       0   165.9    .045       0   195.4     .07       0
#XS Ineff= 2 , 0
           102.2  835.75
Permanent Ineff=
       F       F
Bank Sta=165.9,195.4
XS Rating Curve= 0 ,0
Exp/Cntr=0.3,0.1

Type RM Length L Ch R = 1 ,2601.3  ,224.5,183.5,137.8
XS GIS Cut Line= 4
     1848024.404      482683.447     1847953.733      482776.614
     1847877.124      482719.304     1847795.253      482827.491
#Sta/Elev= 30
       0  840.02     9.7  836.22    19.5  833.73    29.2  832.35      39  831.57
    48.7  831.33    58.5  831.26    87.7  831.57   107.2  831.58   126.5  831.27
   136.1  831.03   145.6  830.27   155.2   828.6   160.7  828.02   164.8  827.59
   174.3     828   175.7  828.14   183.9  828.97   193.5  829.57     203  829.62
   212.6  829.47   241.7   830.9   251.4  831.29   290.1  832.06   299.8  833.01
   309.5  835.94   319.2  840.49   328.9  845.38   338.6  851.39   348.3  858.42
#Mann= 3 , 0 , 0
       0     .07       0   160.7    .045       0   175.7     .07       0
#XS Ineff= 2 , 0
          115.06  833.99
Permanent Ineff=
       F       F
Bank Sta=160.7,175.7
XS Rating Curve= 0 ,0
Exp/Cntr=0.3,0.1

Type RM Length L Ch R = 1 ,2417.8  ,264.6,262.3,260
XS GIS Cut Line= 2
     1847845.034      482541.051     1847698.506      482763.273
#Sta/Elev= 22
       0  882.08     9.5  875.26      19  868.56    28.5  862.17    47.5  850.18
      57  843.92    66.6  833.43      76  825.88    80.2  824.92    85.6  823.69
    95.2  824.22   104.6  825.26   123.6   826.3   142.6   827.1   161.6  828.24
   209.1  830.01   218.6  831.21   228.2  834.61   237.7  839.15   247.2   843.9
   256.7   849.1   266.2  855.57
#Mann= 3 , 0 , 0
       0      .1       0    80.2    .045       0    95.2     .07       0
Bank Sta=80.2,95.2
XS Rating Curve= 0 ,0
Exp/Cntr=0.3,0.1

Type RM Length L Ch R = 1 ,2155.6  ,118.6,91.9,64.1
XS GIS Cut Line= 2
      1847605.45      482415.356     1847478.367      482663.967
#Sta/Elev= 26
       0  875.73     9.6  868.24    19.3  858.93    28.9  846.49    38.5  835.25
    48.1  830.21    57.8   827.8    67.4   824.4      77  821.58    86.6  821.03
    94.4  821.87   105.9  823.11   125.2  823.38   144.4  823.45   163.7  823.91
   173.3  823.97   182.9  823.86   192.6  823.94   202.2  824.48   211.8  825.48
   231.1  828.51   240.7  830.29   250.3  833.15     260  837.37   269.6  842.06
   279.2  846.88
#Mann= 3 , 0 , 0
       0      .1       0      77    .045       0    94.4     .07       0
Bank Sta=77,94.4
XS Rating Curve= 0 ,0
Exp/Cntr=0.3,0.1

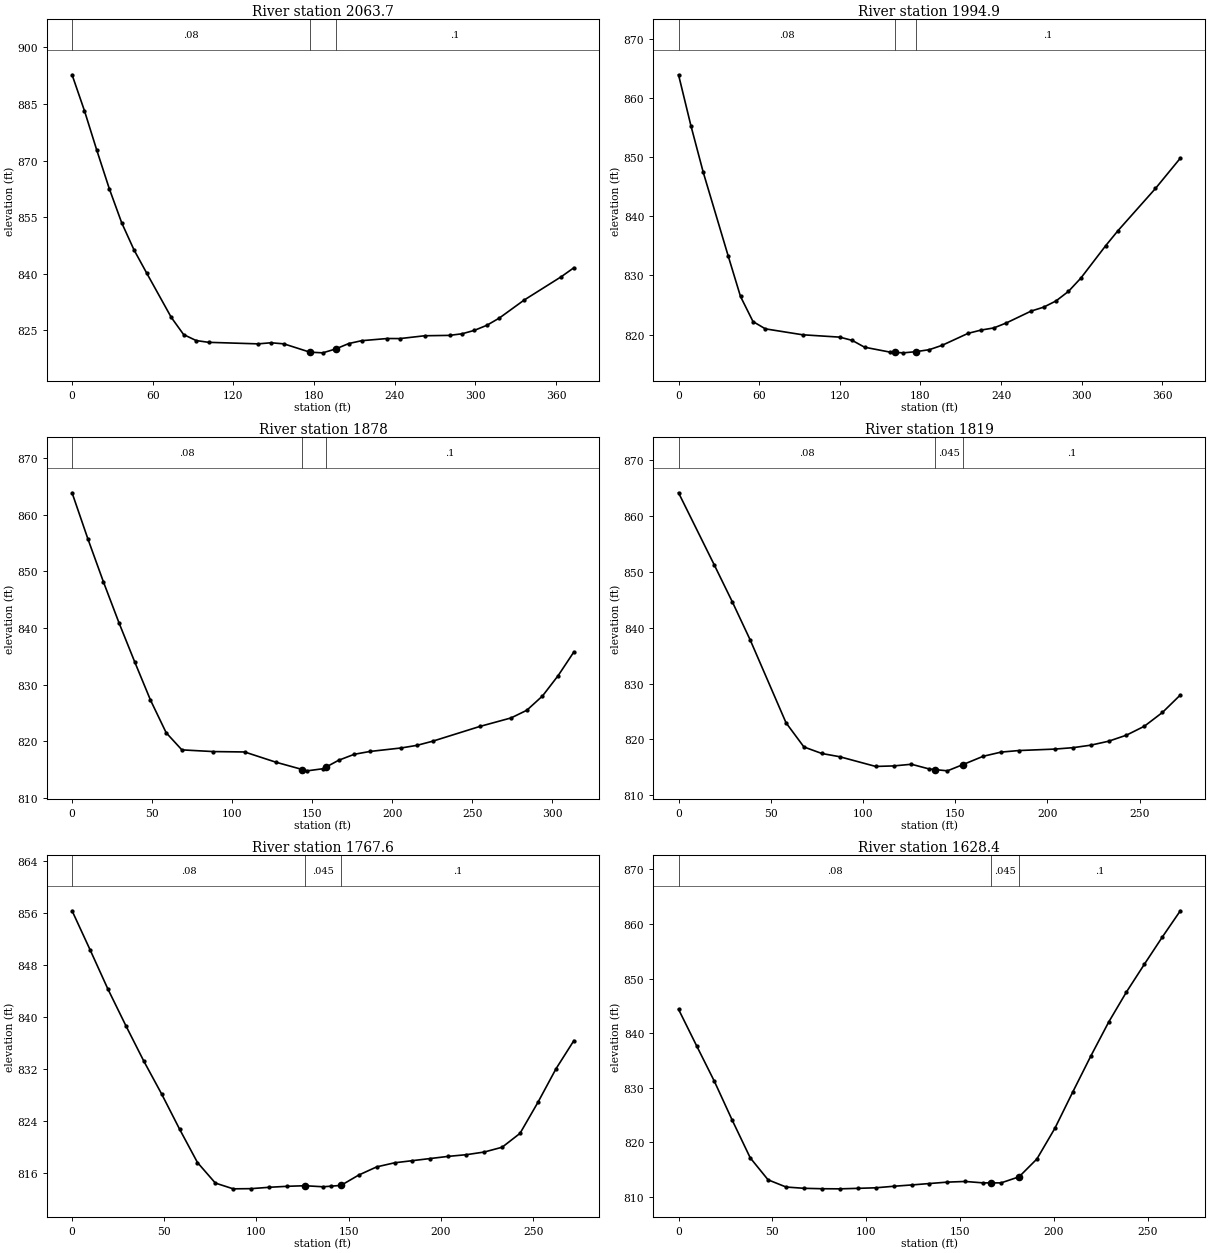
Type RM Length L Ch R = 1 ,2063.7  ,67.9,68.8,66
XS GIS Cut Line= 4
     1847506.255      482305.848     1847447.571      482431.197
     1847497.182      482513.633     1847439.075      482639.514
#Sta/Elev= 30
       0  892.73     9.2  883.21    18.4  872.72    27.7  862.52    36.9   853.5
    46.1  846.28    55.4  840.22    73.8   828.4      83  823.84    92.3  822.26
   101.5  821.79   138.4  821.38     148  821.67   157.6  821.38   176.9  819.18
   186.5     819   196.1  820.03   205.8  821.46   215.4  822.22   234.6   822.8
   243.9  822.78   262.4  823.53   280.8  823.63   290.1  824.05   299.3  824.96
   308.6  826.31   317.8  828.21   336.3  832.99     364   839.2   373.3  841.56
#Mann= 3 , 0 , 0
       0     .08       0   176.9    .045       0   196.1      .1       0
Bank Sta=176.9,196.1
XS Rating Curve= 0 ,0
Exp/Cntr=0.3,0.1

Type RM Length L Ch R = 1 ,1994.9  ,91.8,116.9,146.4
XS GIS Cut Line= 4
     1847452.578      482310.449     1847393.317      482435.526
     1847442.549       482518.19     1847383.864      482643.802
#Sta/Elev= 30
       0  863.89     9.2   855.3    18.4  847.41    36.9  833.33    46.1  826.46
    55.4  822.22    64.6  820.99    92.3  819.99     120  819.59   129.2  819.04
   138.4  817.89   157.6  817.05   161.3  817.01   167.3  816.94   176.3  817.13
   186.5  817.47   196.1  818.21   215.4  820.23     225  820.78   234.6  821.15
   243.9  821.99   262.4     824   271.6  824.65   280.8   825.7   290.1  827.32
   299.3  829.56   317.8  835.04     327  837.59   354.8  844.69   373.3  849.81
#Mann= 3 , 0 , 0
       0     .08       0   161.3    .045       0   176.3      .1       0
Bank Sta=161.3,176.3
XS Rating Curve= 0 ,0
Exp/Cntr=0.3,0.1

Type RM Length L Ch R = 1 ,1878    ,59.6,58.9,58.2
XS GIS Cut Line= 2
     1847368.645      482271.606     1847236.006      482555.634
#Sta/Elev= 27
       0  863.87     9.8   855.8    19.6  848.14    29.4  840.86    39.2  833.98
      49  827.28    58.8  821.52    68.6   818.5    88.2   818.2   107.8  818.13
   127.4  816.32   143.9  815.03   146.9   814.8   156.7  815.17   158.9   815.5
   166.5  816.66   176.3  817.72   186.1  818.22   205.7  818.84   215.5   819.3
   225.3  820.03   254.7  822.63   274.3  824.14   284.1  825.49   293.9  828.01
   303.7  831.61   313.5  835.78
#Mann= 3 , 0 , 0
       0     .08       0   143.9    .045       0   158.9      .1       0
Bank Sta=143.9,158.9
XS Rating Curve= 0 ,0
Exp/Cntr=0.3,0.1

Type RM Length L Ch R = 1 ,1819    ,51.4,51.4,51.4
XS GIS Cut Line= 2
     1847309.639      482248.623     1847201.803      482498.406
#Sta/Elev= 26
       0  864.21    19.4  851.26    29.2  844.63    38.9  837.79    58.3  822.96
      68  818.63    77.7  817.46    87.4  816.88   106.9  815.14   116.6  815.23
   126.3  815.53     136  814.68   139.3  814.57   145.8  814.35   154.3  815.48
   165.2  816.96   174.9  817.71   184.6  817.99     204  818.25   213.8   818.5
   223.5  818.95   233.2  819.66   242.9  820.75   252.6  822.35   262.4  824.82
   272.1  827.95
#Mann= 3 , 0 , 0
       0     .08       0   139.3    .045       0   154.3      .1       0
Bank Sta=139.3,154.3
XS Rating Curve= 0 ,0
Exp/Cntr=0.3,0.1

Type RM Length L Ch R = 1 ,1767.6  ,129.8,139.2,148.5
XS GIS Cut Line= 2
     1847262.972      482226.956     1847155.136      482476.739
#Sta/Elev= 30
       0  856.39     9.7  850.41    19.4  844.33    29.2  838.64    38.9  833.19
    48.6   828.1    58.3  822.69      68  817.54    77.7  814.37    87.4  813.48
    97.2  813.51   106.9  813.72   116.6  813.87   126.3  813.96     136   813.8
   140.4  813.89   145.8  814.01   155.4   815.6   165.2  816.87   174.9   817.5
   184.6  817.83   194.3  818.16     204  818.49   213.8  818.75   223.5  819.16
   233.2   819.9   242.9  822.04   252.6  826.82   262.4     832   272.1  836.35
#Mann= 3 , 0 , 0
       0     .08       0   126.3    .045       0   145.8      .1       0
Bank Sta=126.3,145.8
XS Rating Curve= 0 ,0
Exp/Cntr=0.3,0.1

Type RM Length L Ch R = 1 ,1628.4  ,135.9,147.7,159.1
XS GIS Cut Line= 2
     1847204.062      482188.273     1847008.923      482370.912
#Sta/Elev= 30
       0  844.38     9.6  837.72    19.1  831.19    28.6  824.08    38.2  817.18
    47.7  813.16    57.3  811.84    66.8  811.61    76.4  811.53    85.9  811.51
    95.5   811.6     105   811.7   114.6  811.98   124.1  812.22   133.6  812.48
   143.2  812.74   152.7  812.86   162.3   812.6   166.4   812.6   171.8   812.6
   181.4  813.71   190.9  816.98   200.5  822.61     210  829.24   219.6  835.81
   229.1  842.02   238.6  847.55   248.2  852.66   257.7  857.61   267.3  862.42
#Mann= 3 , 0 , 0
       0     .08       0   166.4    .045       0   181.4      .1       0
Bank Sta=166.4,181.4
XS Rating Curve= 0 ,0
Exp/Cntr=0.3,0.1

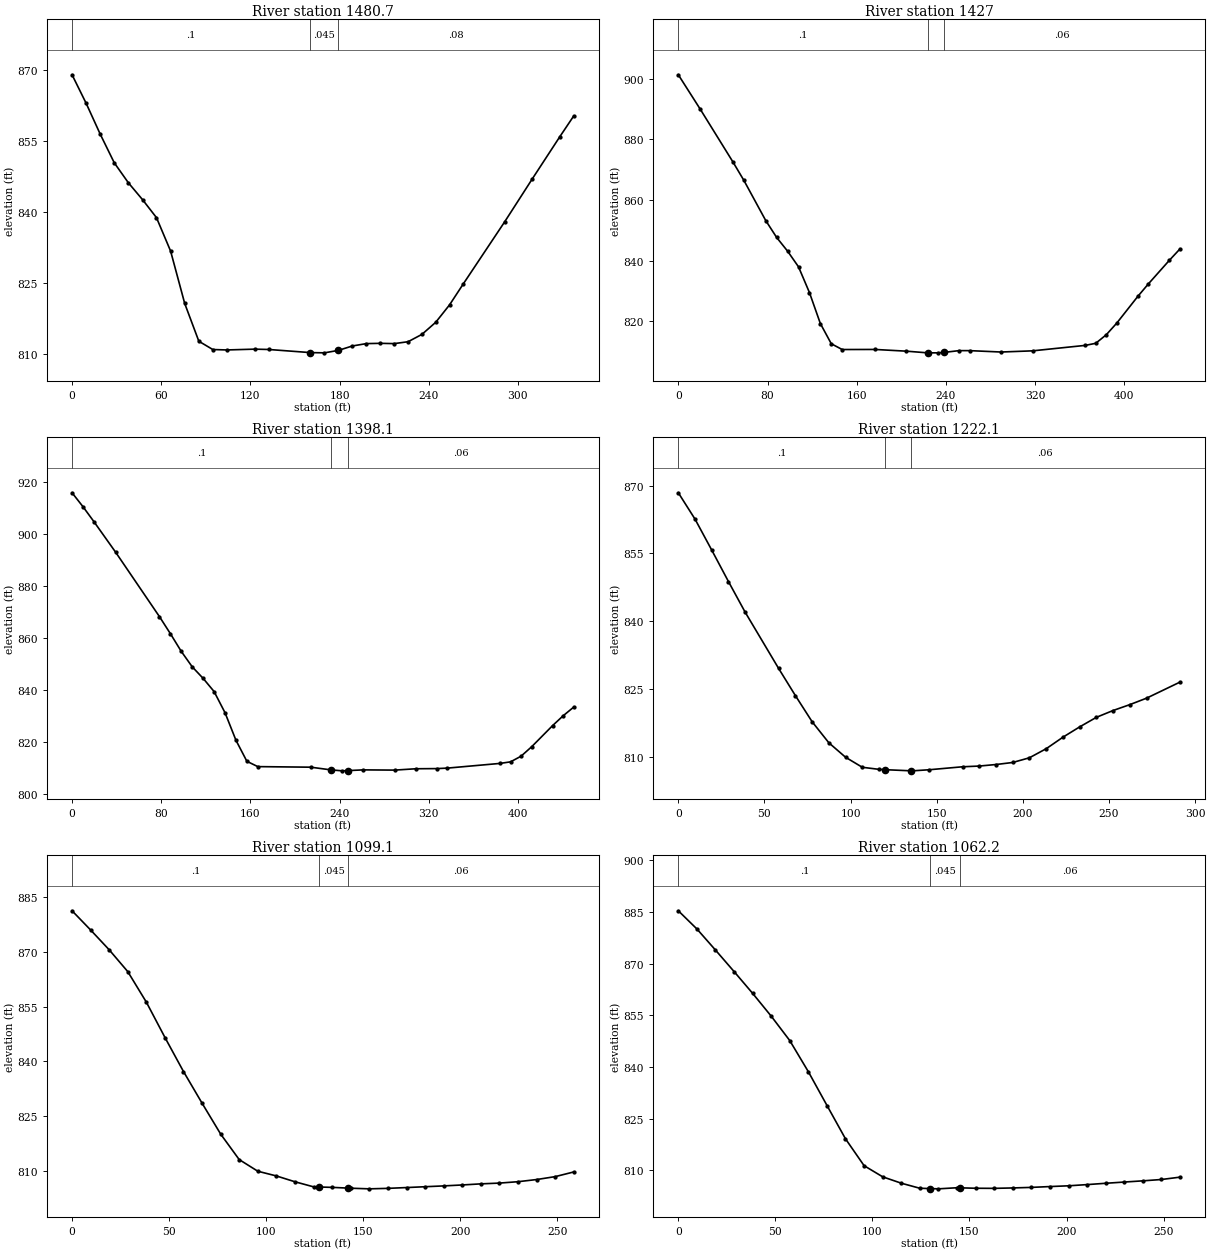
Type RM Length L Ch R = 1 ,1480.7  ,31.9,53.7,76.7
XS GIS Cut Line= 4
     1847170.034      482113.967     1847096.423      482157.023
     1846968.645      482188.273     1846873.506      482262.579
#Sta/Elev= 30
       0   868.9     9.5  862.86      19  856.32    28.4   850.3    37.9  846.07
    47.4  842.52    56.8  838.71    66.3  831.65    75.8  820.57    85.3  812.59
    94.7  810.84   104.1  810.75   122.9  810.92   132.3  810.85   160.4  810.19
   169.8  810.14   179.2  810.66   188.6  811.59     198  812.09   207.4  812.15
   216.8  812.09   226.1  812.49   235.4  814.04   244.7   816.6     254  820.28
   263.2  824.69   291.1  837.84   309.7  846.92   328.2  855.82   337.5  860.18
#Mann= 3 , 0 , 0
       0      .1       0   160.4    .045       0   179.2     .08       0
Bank Sta=160.4,179.2
XS Rating Curve= 0 ,0
Exp/Cntr=0.3,0.1

Type RM Length L Ch R = 1 ,1427    ,28,29,46.3
XS GIS Cut Line= 4
     1847199.193      482068.236     1847048.614      482160.011
     1846960.443       482089.07     1846826.276      482176.986
#Sta/Elev= 30
       0  901.36    19.6  890.04      49  872.57    58.8   866.5    78.4  853.24
    88.2  847.65      98  843.13   107.8  837.96   117.6  829.47   127.4  819.23
   137.2  812.56     147  810.65   176.3  810.68   204.6  810.11   223.5  809.56
   223.7  809.56   232.9  809.56   238.7  809.72   251.8  810.29   261.2  810.29
   289.5  809.83   317.8  810.22     365  812.02   374.4  812.71   383.9  815.55
   393.3   819.4   412.2  828.23   421.6  832.32   440.5  840.14   449.9  843.85
#Mann= 3 , 0 , 0
       0      .1       0   223.7    .045       0   238.7     .06       0
Bank Sta=223.7,238.7
XS Rating Curve= 0 ,0
Exp/Cntr=0.3,0.1

Type RM Length L Ch R = 1 ,1398.1  ,209,176,125
XS GIS Cut Line= 4
     1847207.526      482044.903     1847056.947      482136.677
     1846968.776      482065.736      1846834.61      482153.653
#Sta/Elev= 30
       0  915.71     9.8  910.37    19.6  904.64    39.2  892.84    78.4  868.19
    88.2  861.66      98  854.84   107.8  848.94   117.6   844.5   127.4  839.46
   137.2  831.34     147  820.78   156.8  812.71   166.6  810.67   214.1  810.45
   232.5   809.4   242.4  809.05   247.5  809.14   261.2  809.42   289.5  809.33
   308.4  809.85   327.2  809.91   336.7   810.1   383.9   811.9   393.3   812.5
   402.7  814.66   412.2  818.28     431   826.4   440.5  830.18   449.9  833.48
#Mann= 3 , 0 , 0
       0      .1       0   232.5    .045       0   247.5     .06       0
Bank Sta=232.5,247.5
XS Rating Curve= 0 ,0
Exp/Cntr=0.3,0.1

Type RM Length L Ch R = 1 ,1222.1  ,127.3,123,118.3
XS GIS Cut Line= 2
      1847005.45      481874.384     1846779.756      482058.412
#Sta/Elev= 29
       0  868.45     9.7  862.61    19.4  855.75    29.1  848.78    38.8  841.99
    58.2  829.54      68  823.48    77.7   817.7    87.4  813.04    97.1  809.84
   106.8  807.62   116.5  807.16   119.8  807.09   134.8  806.84   135.9  806.83
   145.6  807.07     165  807.73   174.7  807.89   184.4  808.23   194.1  808.68
   203.8  809.72   213.6  811.74   223.3  814.29     233  816.57   242.7  818.69
   252.4   820.2   262.1   821.5   271.8  822.93   291.2  826.49
#Mann= 3 , 0 , 0
       0      .1       0   119.8    .045       0   134.8     .06       0
Bank Sta=119.8,134.8
XS Rating Curve= 0 ,0
Exp/Cntr=0.3,0.1

Type RM Length L Ch R = 1 ,1099.1  ,36.9,36.9,36.9
XS GIS Cut Line= 2
     1846913.443      481756.792     1846749.276      481956.375
#Sta/Elev= 30
       0  881.17     9.6   875.9    19.1  870.52    28.7  864.54    38.3  856.17
    47.9  846.49    57.4  837.23      67  828.55    76.6  820.09    86.1  813.16
    95.7  809.97   105.3  808.68   114.9  807.08   124.4  805.71   127.3  805.66
     134  805.56   142.3  805.36   143.6  805.33   153.1  805.16   162.7  805.29
   172.3  805.51   181.9  805.74   191.4  805.96     201  806.22   210.6  806.52
   220.1  806.73   229.7  807.11   239.3   807.7   248.9   808.5   258.4  809.77
#Mann= 3 , 0 , 0
       0      .1       0   127.3    .045       0   142.3     .06       0
Bank Sta=127.3,142.3
XS Rating Curve= 0 ,0
Exp/Cntr=0.3,0.1

Type RM Length L Ch R = 1 ,1062.2  ,199.5,197.7,195.9
XS GIS Cut Line= 2
     1846889.693      481728.042     1846725.526      481927.625
#Sta/Elev= 30
       0  885.35     9.6  880.06    19.1  873.98    28.7  867.73    38.3  861.38
    47.9  854.74    57.4   847.7      67  838.64    76.6  828.84    86.1   819.2
    95.7  811.39   105.3  808.15   114.9   806.3   124.4  804.84   129.9  804.74
     134  804.67   143.6  804.99   144.9  804.97   153.1  804.84   162.7  804.81
   172.3  804.93   181.9  805.09   191.4  805.33     201  805.55   210.6   805.9
   220.1  806.28   229.7  806.64   239.3  806.99   248.9  807.38   258.4  808.06
#Mann= 3 , 0 , 0
       0      .1       0   129.9    .045       0   144.9     .06       0
Bank Sta=129.9,144.9
XS Rating Curve= 0 ,0
Exp/Cntr=0.3,0.1

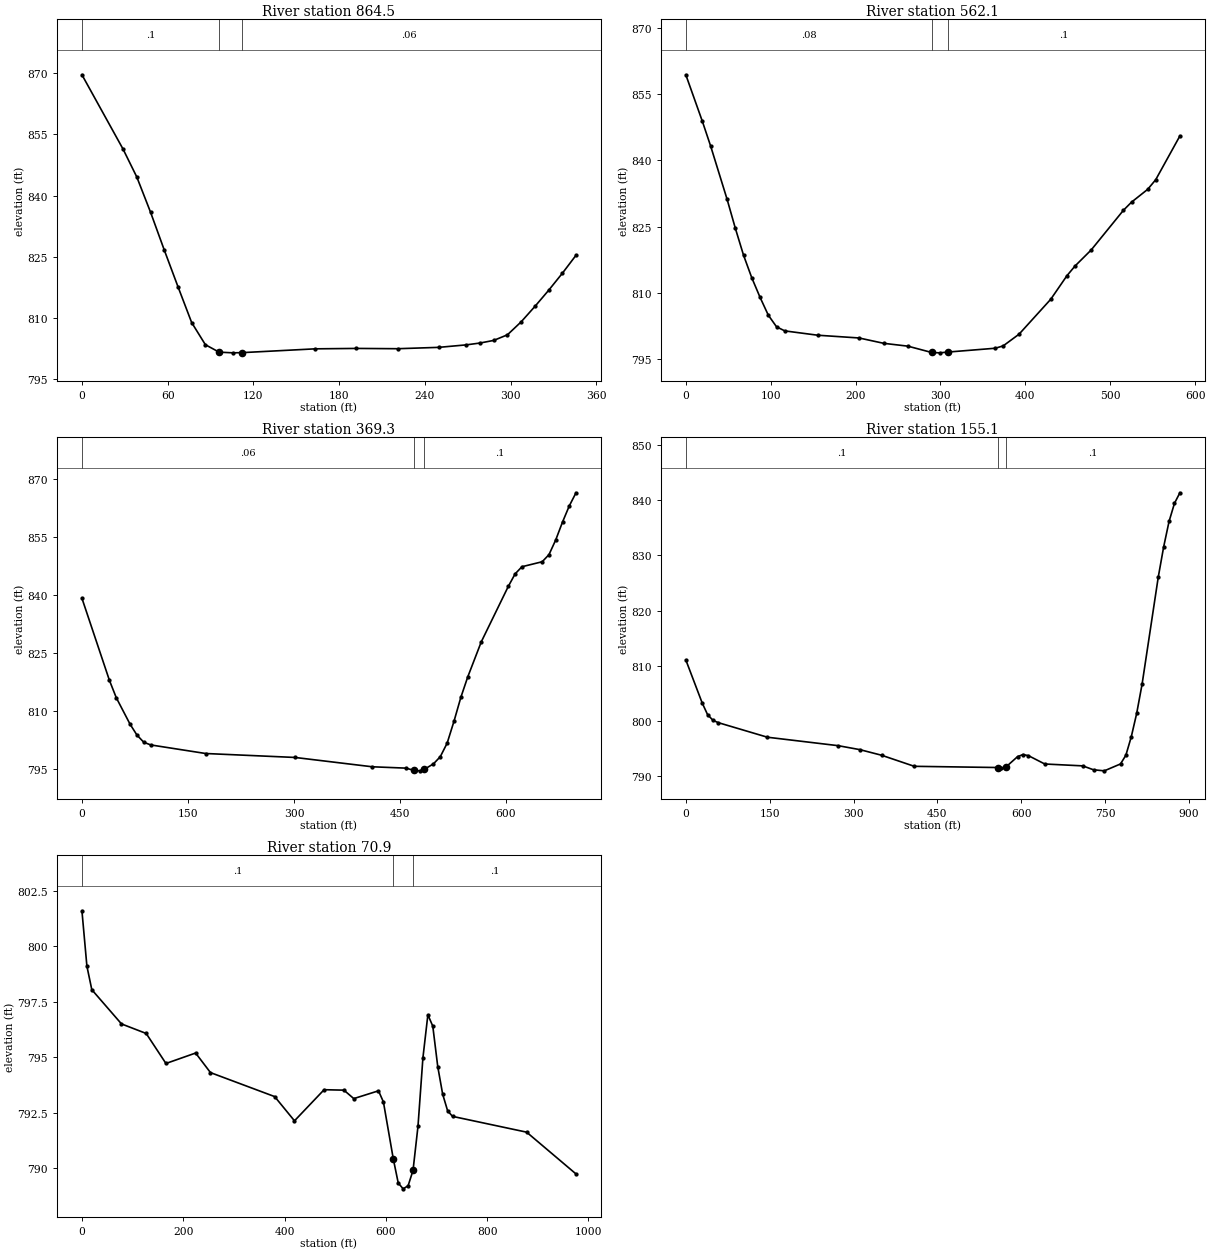
Type RM Length L Ch R = 1 ,864.5   ,307.6,302.4,297.2
XS GIS Cut Line= 2
     1846714.478       481617.44     1846517.256      481901.467
#Sta/Elev= 24
       0  869.56    28.8  851.36    38.4  844.55      48  835.95    57.6   826.7
    67.2  817.72    76.8  808.93    86.4  803.51      96  801.69   105.7  801.52
   112.1  801.57   163.3   802.5   192.1   802.6   220.9  802.53   249.7  802.86
     269  803.47   278.6  803.92   288.2  804.56   297.8  805.93   307.4   809.1
     317  812.86   326.6   816.8   336.2  820.97   345.8  825.39
#Mann= 3 , 0 , 0
       0      .1       0      96    .045       0   112.1     .06       0
Bank Sta=96,112.1
XS Rating Curve= 0 ,0
Exp/Cntr=0.3,0.1

Type RM Length L Ch R = 1 ,562.1   ,191.3,192.8,194.2
XS GIS Cut Line= 4
      1846655.45      481518.829     1846413.089      481502.162
     1846345.034      481676.467     1846215.173      481755.634
#Sta/Elev= 30
       0  859.34    19.4  848.87    29.2  843.26    48.6  831.22    58.3  824.68
      68  818.57    77.7  813.47    87.5  809.03    97.2  805.01   106.9  802.38
   116.6  801.46   155.5  800.48   204.1  799.86   233.2  798.65   261.6  798.01
   289.7  796.58   299.1   796.5   308.4  796.67   364.6  797.54   373.9  798.07
   392.6  800.71     430  808.62   449.1  813.95   458.6  816.13   477.6  819.75
   515.6  828.72   525.1  830.55   544.1  833.44   553.6  835.62   582.1  845.51
#Mann= 3 , 0 , 0
       0     .08       0   289.7    .045       0   308.4      .1       0
Bank Sta=289.7,308.4
XS Rating Curve= 0 ,0
Exp/Cntr=0.3,0.1

Type RM Length L Ch R = 1 ,369.3   ,199.6,214.2,229
XS GIS Cut Line= 5
       1846636.7      481475.079     1846319.339      481427.162
     1846231.145      481471.606     1846173.506      481594.523
     1846113.784      481725.079
#Sta/Elev= 30
       0  839.06    38.9  817.83    48.6  813.34    68.1   806.5    77.8   803.7
    87.5  801.83    97.3  801.14   175.1  798.92   301.5   797.9   410.7  795.49
   458.5  795.14   469.1  794.59   477.9  794.44   484.1   794.8   497.3  796.24
     507   798.1   516.7   801.6   526.4  807.27   536.1  813.45   545.8   818.7
     565   827.8   603.3  842.16   612.9  845.37   622.5  847.21   651.2   848.5
   660.8  850.35   670.3  854.13   679.9  858.75   689.5  862.94     699  866.33
#Mann= 3 , 0 , 0
       0     .06       0   469.1    .045       0   484.1      .1       0
Bank Sta=469.1,484.1
XS Rating Curve= 0 ,0
Exp/Cntr=0.3,0.1

Type RM Length L Ch R = 1 ,155.1   ,83.7,84.2,84.1
XS GIS Cut Line= 4
     1846595.297      481426.154     1846183.593      481308.442
      1845951.04      481430.173     1845918.058      481620.394
#Sta/Elev= 30
       0  811.07    29.2  803.29    38.9  801.16    48.7  800.11    58.4  799.69
     146  797.06   272.5  795.53   311.4  794.81   350.4  793.79   408.7  791.79
     558  791.57   564.3   791.4     573   791.7   593.5  793.55   603.2  793.92
   612.9  793.72   642.1  792.21     710  791.87   729.3  791.16   748.6  790.97
   777.6  792.22   787.2   793.8   796.9  797.16   806.5  801.37   816.2  806.68
   845.1  826.06   854.8  831.56   864.4  836.15   874.1  839.44   883.8  841.35
#Mann= 3 , 0 , 0
       0      .1       0     558    .045       0     573      .1       0
Bank Sta=558,573
XS Rating Curve= 0 ,0
Exp/Cntr=0.3,0.1

Type RM Length L Ch R = 1 ,70.9    ,73.2,70.9,68.7
XS GIS Cut Line= 3
     1846647.225      481307.026     1846092.537      481264.491
     1845719.273      481455.463
#Sta/Elev= 30
       0  801.59     9.8   799.1    19.5  798.04    78.1   796.5   126.9  796.07
   165.9  794.72   224.5  795.19   253.8  794.31   380.6  793.23   419.7  792.14
   478.2  793.54   517.3  793.52   536.8  793.14   585.6  793.49   595.3  792.99
   614.8  790.43   624.6  789.34   634.3  789.08   644.1  789.22   653.8  789.91
   663.6   791.9   673.3  794.97   683.1  796.91   692.8   796.4   702.6  794.58
   712.3  793.34   722.1  792.59   731.8  792.34   878.1  791.63   975.6  789.75
#Mann= 3 , 0 , 0
       0      .1       0   614.8    .045       0   653.8      .1       0
Bank Sta=614.8,653.8
XS Rating Curve= 0 ,0
Exp/Cntr=0.3,0.1

Chan Stop Cuts=-1
Use User Specified Reach Order=0
Composite Channel Slope=5